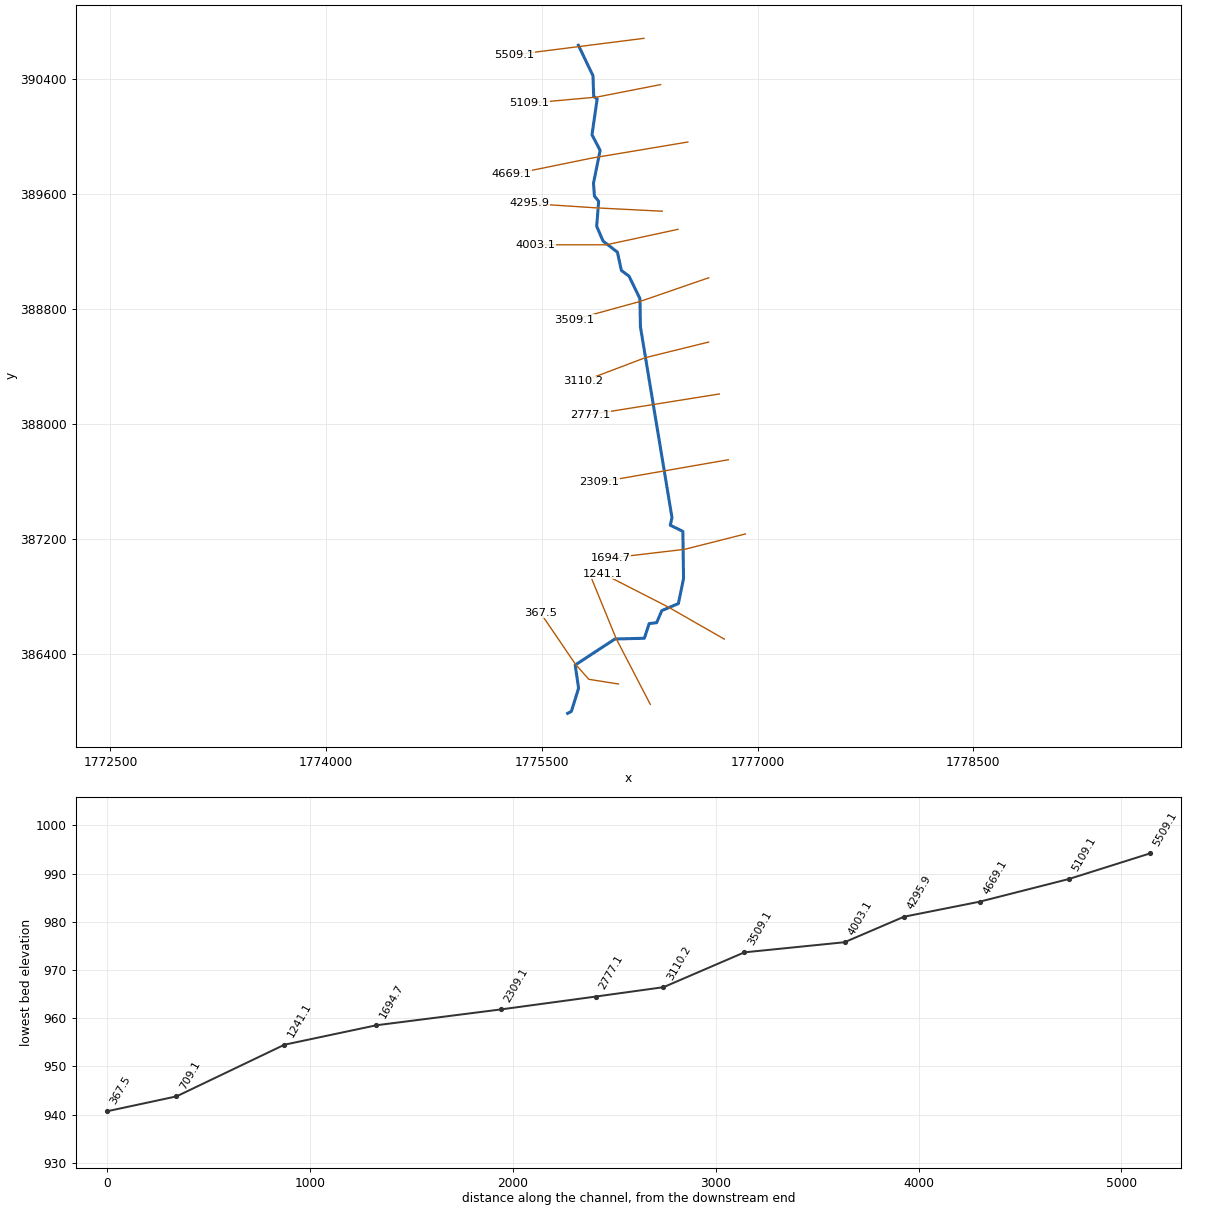
--- PnthrLckRn.prj (project) ---

Proj Title=PnthrLckRn
Current Plan=p01
Geom File=g01
Flow File=f01
Plan File=p01
DSS Export Rating Curves=0
DSS Export Rating Curve Sorted=0
DSS Export Volume Flow Curves=0
DXF OffsetX=0
DXF OffsetY=0
DXF ScaleX=0
DXF ScaleY=0

--- PnthrLckRn.p01 (plan) ---

Plan Title=Floodplain
Program Version=4.00
Geom File=g01
Flow File=f01
K Sum by GR=0
Std Step Tol=0.01
Critical Tol=0.01
Num of Std Step Trials=20
Max Error Tol=0.3
Flow Tol Ratio=0.001
Split Flow NTrial=30
Split Flow Tol=0.02
Split Flow Ratio=0.02
Log Output Level=0
Friction Slope Method=1
Unsteady Friction Slope Method=2
Unsteady Bridges Friction Slope Method=1
Global Log Level=0
CheckData=False
Run HTab=0
Run UNet=0
Run PostProcess=0
UNET Theta=0
UNET Theta Warmup=0
UNET ZTol=0
UNET ZSATol=0
UNET MxIter=0
UNET MaxInSteps=0
UNET DtIC=0
UNET DtMin=0
UNET MaxCRTS=0
UNET WFStab=0
UNET SFStab=0
UNET WFX=0
UNET SFX=0
UNET DSS MLevel=0
UNET DZMax Abort=0
UNET Convert EG Bridges=0
UNET Use Existing IB Tables=0
UNET Froude Limit=0
UNET Froude Power=0
Write IC File=0
Echo Input=False
Echo Output=False
Write Detailed=0

--- PnthrLckRn.f01 (steady flow) ---

Flow Title=NFF Regression Equation
Program Version=4.00
Number of Profiles=1
Profile Names=P100yr
River Rch & RM=PnthrLckRn,Main      ,5509.1
511.6358
River Rch & RM=PnthrLckRn,Main      ,5109.1
511.6358
River Rch & RM=PnthrLckRn,Main      ,5109.1
855.2736
River Rch & RM=PnthrLckRn,Main      ,4295.9
889.1939
River Rch & RM=PnthrLckRn,Main      ,367.5
986.0567
Boundary for River Rch & Prof#=PnthrLckRn,Main      ,1
Up Type=0
Dn Type=3
Dn Slope=0.011428

--- PnthrLckRn.g01 (geometry) ---

Geom Title=USGS 3m DEM
Program Version=4.00

River Reach=PnthrLckRn     ,Main
Reach XY= 30
     1775753.535      390631.847     1775854.960      390420.401
     1775860.117      390276.000     1775884.184      390258.809
     1775848.083      390009.544     1775904.813      389901.243
     1775858.398      389672.607     1775865.274      389583.216
     1775894.498      389547.115     1775880.746      389373.490
     1775925.441      389270.345     1776025.147      389192.987
     1776052.652      389065.776     1776105.943      389026.238
     1776181.582      388869.803     1776185.020      388673.829
     1776404.451      387347.072     1776392.569      387294.710
     1776479.967      387251.976     1776484.803      386923.671
     1776448.790      386749.429     1776333.808      386701.269
     1776297.623      386616.729     1776245.824      386610.954
     1776212.244      386508.504     1776007.818      386503.524
     1775731.359      386322.649     1775754.888      386160.891
     1775704.890      386000.604     1775678.975      385986.314

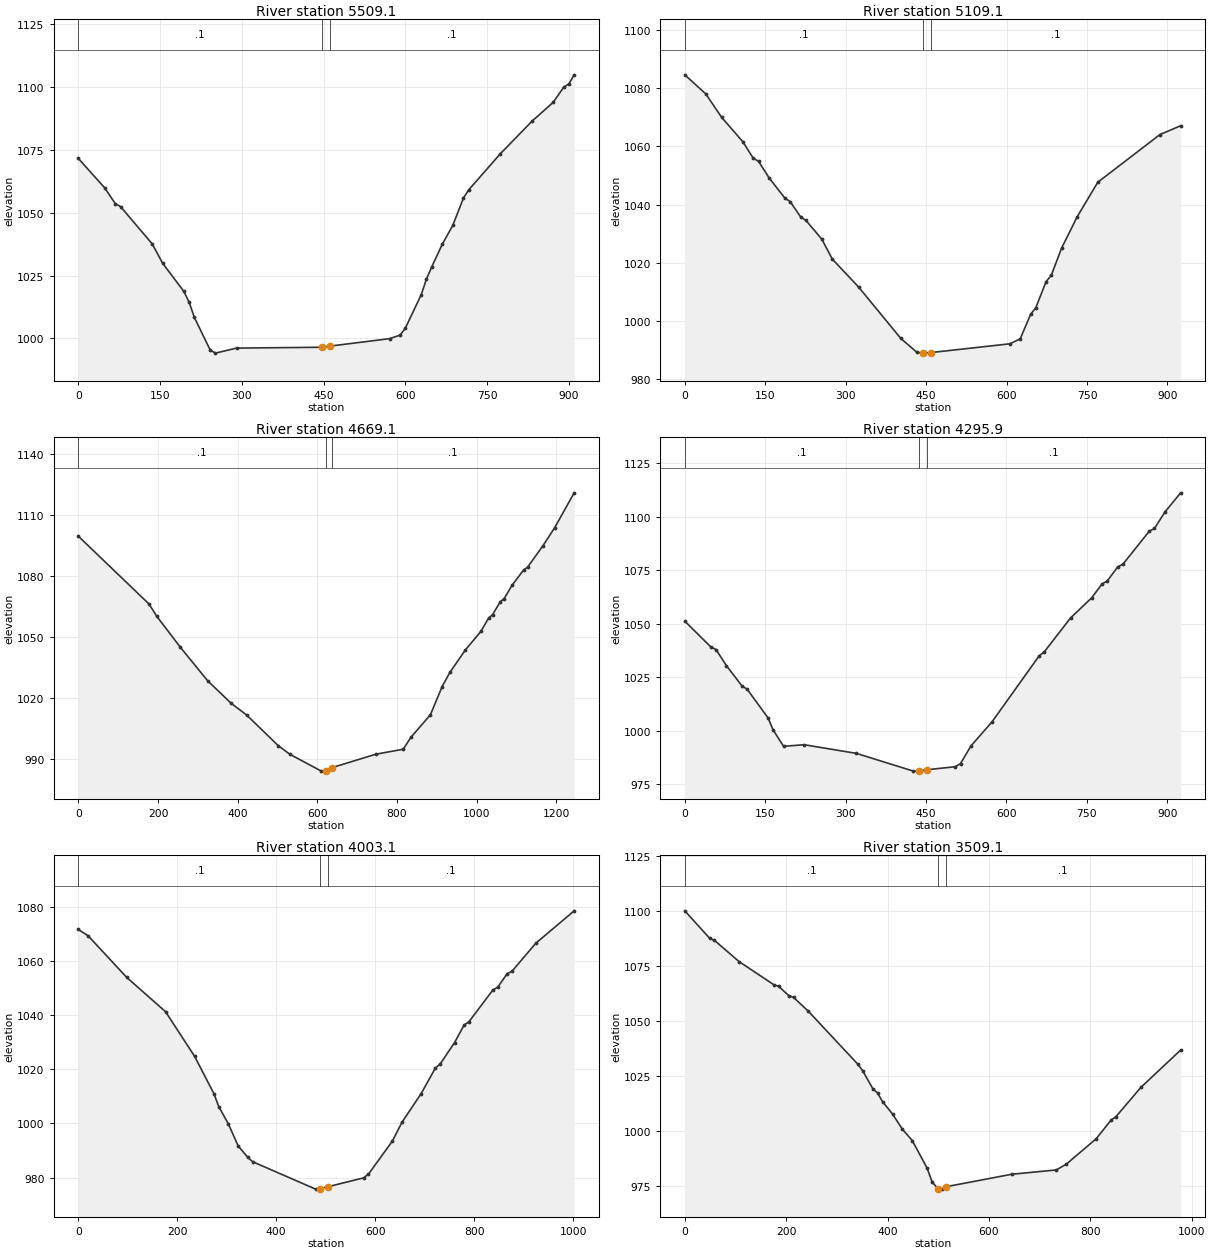
Type RM Length L Ch R = 1 ,5509.1,414.254,400,380.662
XS GIS Cut Line= 3
     1776209.346      390680.116     1775757.960      390622.879
     1775306.575      390565.642
#Sta/Elev= 30
       0 1071.59    48.4 1059.89    67.8 1053.63    77.4 1052.45   135.5 1037.64
   154.9 1029.87   193.6 1018.74   203.3 1014.44   213.0 1008.38   242.0  995.41
   251.7  994.18   290.4  996.18   447.5  996.52   462.5  996.99   571.2  999.93
   590.5 1001.34   600.2 1004.12   629.3 1017.40   638.9 1023.62   648.6 1028.48
   668.0 1037.50   687.3 1045.00   706.7 1055.81   716.4 1059.10   774.5 1073.44
   832.6 1086.40   871.3 1093.86   890.6 1099.84   900.3 1101.24   910.0 1104.84
#Mann= 3 , 0 , 0
       0     0.1       0   447.5   0.045       0   462.5     0.1       0
Bank Sta=   447.5,   462.5
Exp/Cntr=0.3,0.1

Type RM Length L Ch R = 1 ,5109.1,439.835,440.019,481.618
XS GIS Cut Line= 3
     1776325.080      390358.466     1775881.615      390271.652
     1775410.847      390229.019
#Sta/Elev= 30
       0 1084.64    39.3 1078.05    68.8 1069.99   108.1 1061.65   127.7 1055.92
   137.5 1054.90   157.2 1049.18   186.6 1042.22   196.5 1041.01   216.1 1035.72
   225.9 1034.54   255.4 1028.12   275.1 1021.22   324.2 1011.60   402.8  993.93
   432.2  989.26   442.1  988.87   444.4  988.87   459.4  989.07   606.2  992.08
   625.5  993.78   644.8 1002.23   654.5 1004.47   673.8 1013.51   683.4 1015.64
   702.7 1025.04   731.6 1035.75   770.2 1047.69   886.0 1064.08   924.6 1067.11
#Mann= 3 , 0 , 0
       0     0.1       0   444.4   0.045       0   459.4     0.1       0
Bank Sta=   444.4,   459.4
Exp/Cntr=0.3,0.1

Type RM Length L Ch R = 1 ,4669.1,379.36,373.152,367.636
XS GIS Cut Line= 3
     1776514.764      389959.214     1775845.144      389847.086
     1775290.773      389734.026
#Sta/Elev= 30
       0 1099.70   177.1 1066.41   196.8 1060.35   255.8 1045.15   324.7 1028.59
   383.8 1017.50   423.1 1011.66   501.8  996.70   531.3  992.42   610.1  984.16
   621.4  984.43   636.4  985.86   747.2  992.50   815.5  994.92   835.0 1000.81
   883.8 1011.87   913.1 1025.67   932.6 1032.67   971.6 1043.75  1010.6 1052.88
  1030.1 1059.49  1039.9 1061.12  1059.4 1067.49  1069.1 1069.04  1088.6 1075.52
  1117.9 1083.10  1127.7 1084.46  1166.7 1095.08  1196.0 1103.93  1244.7 1121.02
#Mann= 3 , 0 , 0
       0     0.1       0   621.4   0.045       0   636.4     0.1       0
Bank Sta=   621.4,   636.4
Exp/Cntr=0.3,0.1

Type RM Length L Ch R = 1 ,4295.9,288.727,292.837,289.155
XS GIS Cut Line= 3
     1776336.549      389478.032     1775881.524      389501.061
     1775413.214      389531.681
#Sta/Elev= 30
       0 1051.19    48.5 1039.15    58.2 1037.91    77.6 1030.41   106.6 1020.90
   116.3 1019.35   155.1 1006.01   164.8 1000.31   184.2  992.66   223.0  993.38
   319.9  989.35   426.5  981.04   436.5  981.09   451.5  981.69   504.5  983.10
   514.3  984.57   533.8  992.84   572.9 1004.03   660.9 1034.92   670.7 1036.88
   719.6 1052.69   758.7 1062.02   778.3 1068.57   788.0 1069.97   807.6 1076.57
   817.4 1077.86   866.3 1093.25   876.0 1094.53   895.6 1102.23   924.9 1111.21
#Mann= 3 , 0 , 0
       0     0.1       0   436.5   0.045       0   451.5     0.1       0
Bank Sta=   436.5,   451.5
Exp/Cntr=0.3,0.1

Type RM Length L Ch R = 1 ,4003.1,484.575,493.992,507.988
XS GIS Cut Line= 3
     1776446.105      389352.131     1775948.641      389244.548
     1775455.515      389244.548
#Sta/Elev= 30
       0 1071.65    19.6 1069.32    97.9 1053.92   176.2 1041.29   234.9 1024.82
   274.1 1010.98   283.8 1006.24   303.4  999.78   323.0  991.71   342.6  987.47
   352.4  985.86   479.6  975.75     489  975.96     504  976.61   576.6  979.91
   586.3  981.27   634.7  993.48   654.0 1000.41   692.7 1010.98   721.7 1020.49
   731.4 1021.98   760.4 1029.86   779.7 1036.36   789.4 1037.54   837.7 1049.27
   847.4 1050.30   866.7 1055.27   876.4 1056.20   924.7 1066.57  1002.1 1078.52
#Mann= 3 , 0 , 0
       0     0.1       0     489   0.045       0     504     0.1       0
Bank Sta=     489,     504
Exp/Cntr=0.3,0.1

Type RM Length L Ch R = 1 ,3509.1,401.243,398.895,400.338
XS GIS Cut Line= 3
     1776659.660      389015.187     1776179.912      388849.757
     1775725.934      388725.071
#Sta/Elev= 30
       0 1100.22    48.8 1087.81    58.6 1086.76   107.3 1077.10   175.7 1066.61
   185.4 1065.83   204.9 1061.71   214.7 1060.83   244.0 1054.50   341.6 1030.42
   351.3 1027.36   370.8 1019.40   380.6 1017.26   390.4 1013.36   409.9 1007.80
   429.4 1000.86   448.9  995.72   478.2  983.14   488.0  976.92     500  973.73
   507.5  973.65     515  974.72   644.8  980.41   733.1  982.37   752.7  985.02
   811.5  996.52   840.9 1005.00   850.8 1006.64   899.8 1019.91   978.3 1036.90
#Mann= 3 , 0 , 0
       0     0.1       0     500   0.045       0     515     0.1       0
Bank Sta=     500,     515
Exp/Cntr=0.3,0.1

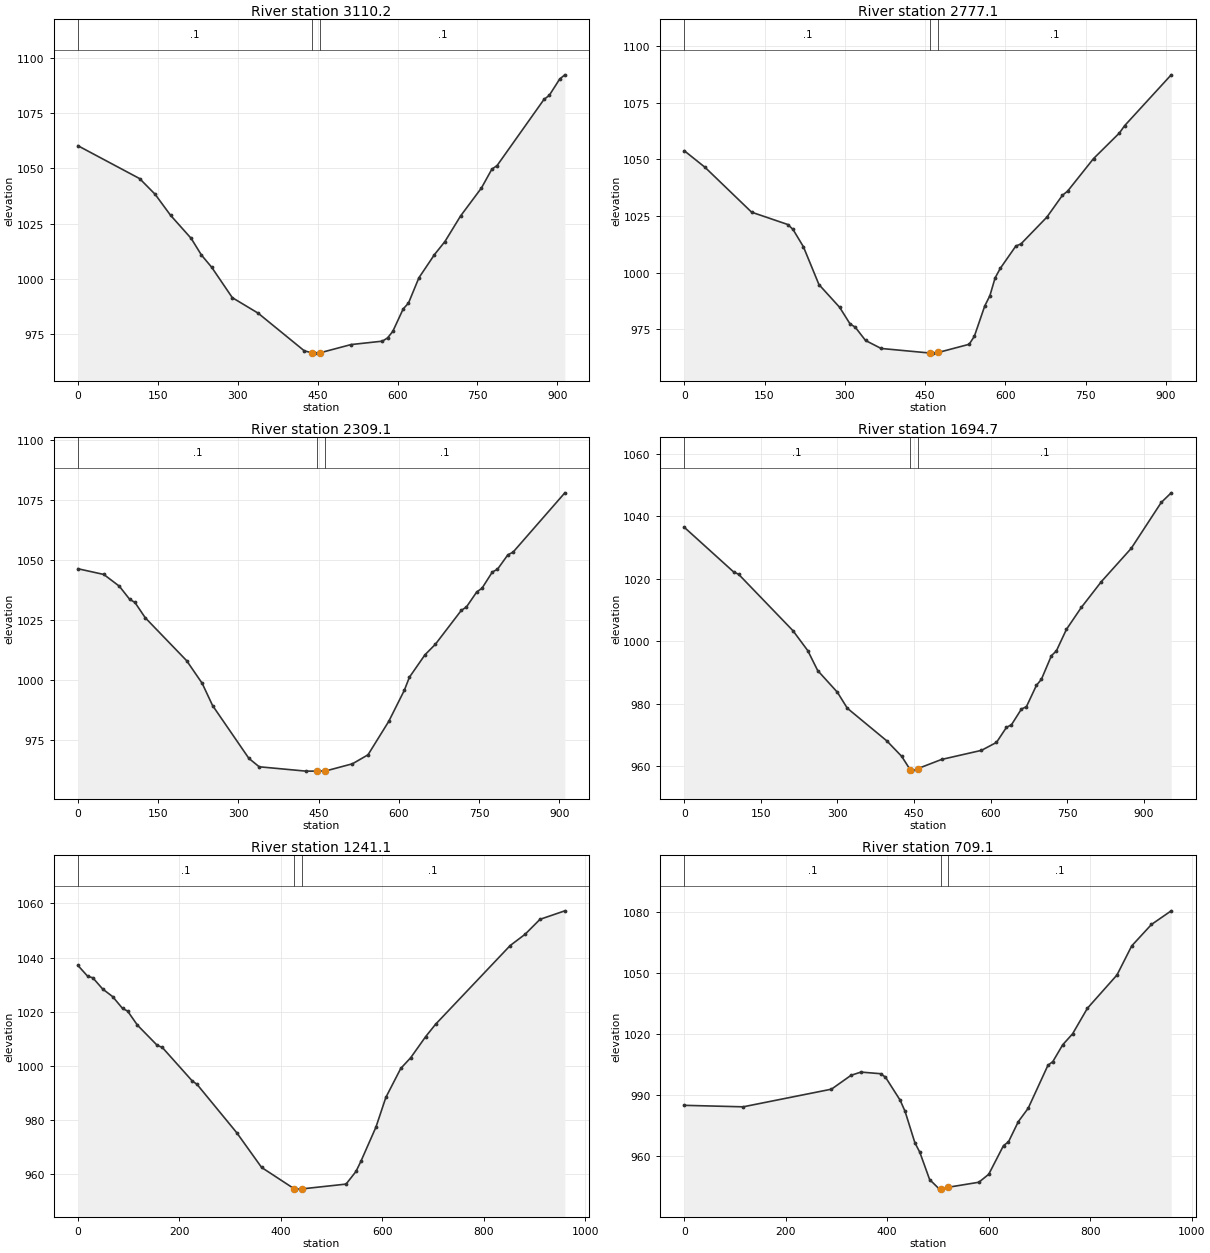
Type RM Length L Ch R = 1 ,3110.2,335.129,333.122,328.999
XS GIS Cut Line= 3
     1776658.957      388568.090     1776218.073      388459.273
     1775787.968      388296.060
#Sta/Elev= 30
       0 1060.19   115.9 1045.32   144.9 1038.25   173.9 1028.75   212.6 1018.30
   231.9 1010.77   251.2 1005.22   289.9  991.49   338.2  984.51   425.1  967.44
   439.9  966.55   444.5  966.42   454.9  966.59   512.8  970.29   571.6  971.83
   581.4  973.31   591.1  976.25   610.7  986.43   620.5  989.00   640.1 1000.46
   669.4 1010.98   689.0 1016.87   718.4 1028.44   757.5 1041.07   777.1 1049.59
   786.9 1051.21   875.0 1081.14   884.8 1082.93   904.4 1090.32   914.1 1092.23
#Mann= 3 , 0 , 0
       0     0.1       0   439.9   0.045       0   454.9     0.1       0
Bank Sta=   439.9,   454.9
Exp/Cntr=0.3,0.1

Type RM Length L Ch R = 1 ,2777.1,467.661,467.983,468.306
XS GIS Cut Line= 3
     1776733.436      388207.188     1776284.128      388135.442
     1775834.820      388063.696
#Sta/Elev= 30
       0 1053.84    38.7 1046.54   125.9 1026.70   193.6 1021.25   203.3 1019.07
   222.7 1011.43   251.7  994.75   290.4  984.70   309.8  977.39   319.5  975.94
   338.8  970.06   367.9  966.54     460  964.50   464.7  964.48     475  964.79
   532.4  968.38   542.1  971.90   561.5  985.27   571.2  989.87   580.9  997.69
   590.5 1001.87   619.6 1011.73   629.3 1012.72   677.7 1024.53   706.7 1034.15
   716.4 1035.99   764.8 1050.35   813.2 1061.66   822.9 1064.88   910.0 1087.34
#Mann= 3 , 0 , 0
       0     0.1       0     460   0.045       0     475     0.1       0
Bank Sta=     460,     475
Exp/Cntr=0.3,0.1

Type RM Length L Ch R = 1 ,2309.1,614.179,614.398,613.536
XS GIS Cut Line= 3
     1776796.063      387749.934     1776347.829      387671.758
     1775899.595      387593.583
#Sta/Elev= 30
       0 1046.39    48.4 1044.00    77.4 1039.10    96.8 1033.60   106.5 1032.33
   125.9 1025.90   203.3 1007.95   232.3  998.49   251.7  989.22   319.5  967.15
   338.8  963.63   426.0  961.81   447.5  961.81   462.5  961.85   513.1  964.88
   542.1  968.62   580.9  982.60   609.9  995.53   619.6 1001.08   648.6 1010.42
   668.0 1014.81   716.4 1028.96   726.1 1030.41   745.4 1036.70   755.1 1038.22
   774.5 1045.02   784.1 1046.17   803.5 1052.20   813.2 1053.31   910.0 1078.11
#Mann= 3 , 0 , 0
       0     0.1       0   447.5   0.045       0   462.5     0.1       0
Bank Sta=   447.5,   462.5
Exp/Cntr=0.3,0.1

Type RM Length L Ch R = 1 ,1694.7,464.371,453.546,445.837
XS GIS Cut Line= 3
     1776914.919      387233.878     1776492.620      387127.029
     1775977.791      387066.401
#Sta/Elev= 30
       0 1036.46    96.8 1022.17   106.5 1021.43   213.0 1003.40   242.0  997.03
   261.4  990.67   300.1  983.71   319.4  978.63   396.9  968.18   425.9  963.26
   442.7  958.97   445.4  958.52   457.7  959.33   504.1  962.25   582.3  965.16
   611.7  967.70   631.2  972.50   641.0  973.33   660.6  978.37   670.3  979.10
   689.9  985.92   699.7  987.87   719.3  995.41   729.0  996.93   748.6 1003.79
   777.9 1010.83   817.1 1019.07   875.7 1029.72   934.4 1044.37   954.0 1047.46
#Mann= 3 , 0 , 0
       0     0.1       0   442.7   0.045       0   457.7     0.1       0
Bank Sta=   442.7,   457.7
Exp/Cntr=0.3,0.1

Type RM Length L Ch R = 1 ,1241.1,545.674,532.057,509.177
XS GIS Cut Line= 3
     1776768.292      386502.616     1776377.436      386726.187
     1775923.504      386958.377
#Sta/Elev= 30
       0 1037.09    19.6 1033.02    29.4 1032.53    48.9 1028.36    68.5 1025.57
    88.1 1021.19    97.9 1020.25   117.5 1015.01   156.6 1007.54   166.4 1006.81
   225.1  994.50   234.9  993.16   313.2  975.31   362.2  962.49   426.1  954.66
   430.7  954.48   441.1  954.55   528.7  956.34   548.3  961.00   558.1  964.80
   587.6  977.35   607.2  988.36   636.6  999.05   656.2 1003.01   685.6 1010.77
   705.2 1015.35   852.3 1044.42   881.7 1048.58   911.1 1054.10   960.1 1057.24
#Mann= 3 , 0 , 0
       0     0.1       0   426.1   0.045       0   441.1     0.1       0
Bank Sta=   426.1,   441.1
Exp/Cntr=0.3,0.1

Type RM Length L Ch R = 1 ,709.1,338.962,341.542,346.709
XS GIS Cut Line= 3
     1776253.416      386049.381     1776017.200      386504.275
     1775847.769      386918.077
#Sta/Elev= 30
       0  984.90   116.1  984.17   290.1  992.83   328.8  999.65   348.2 1001.22
   386.8 1000.43   396.5  998.75   425.5  987.41   435.2  981.93   454.5  966.55
   464.2  961.88   483.6  948.45   502.9  943.76   505.1  943.81   520.1  944.67
   580.6  947.14   600.1  951.06   629.2  965.15   638.9  966.92   658.4  976.90
   677.8  983.45   716.7 1004.53   726.4 1006.38   745.9 1014.64   765.3 1019.99
   794.5 1032.54   852.8 1048.88   881.9 1063.18   920.8 1073.70   959.7 1080.39
#Mann= 3 , 0 , 0
       0     0.1       0   505.1   0.045       0   520.1     0.1       0
Bank Sta=   505.1,   520.1
Exp/Cntr=0.3,0.1

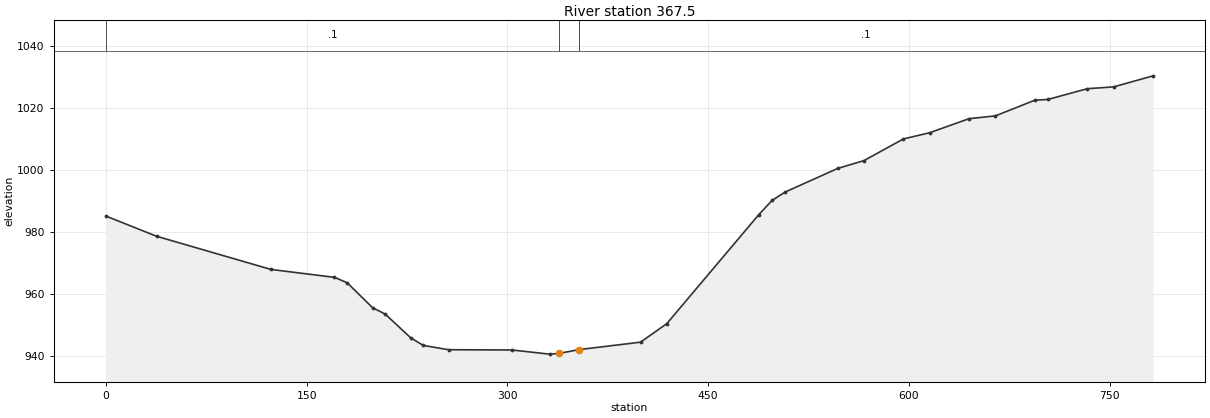
Type RM Length L Ch R = 1 ,367.5,369.354,367.528,365.427
XS GIS Cut Line= 4
     1776032.178      386190.597     1775826.030      386223.254
     1775732.141      386329.390     1775489.254      386686.576
#Sta/Elev= 30
       0  985.20    37.9  978.69   123.3  967.99   170.8  965.44   180.3  963.69
   199.2  955.67   208.7  953.59   227.6  945.99   237.1  943.49   256.0  942.10
   303.2  942.02   331.5  940.68   338.4  940.89   353.4  942.13   399.5  944.54
   419.1  950.52   487.9  985.70   497.7  990.23   507.5  992.95   546.8 1000.57
   566.4 1003.09   595.8 1010.06   615.5 1012.08   644.9 1016.61   664.6 1017.51
   694.0 1022.56   703.8 1022.81   733.3 1026.28   752.9 1026.86   782.4 1030.43
#Mann= 3 , 0 , 0
       0     0.1       0   338.4   0.045       0   353.4     0.1       0
Bank Sta=   338.4,   353.4
Exp/Cntr=0.3,0.1